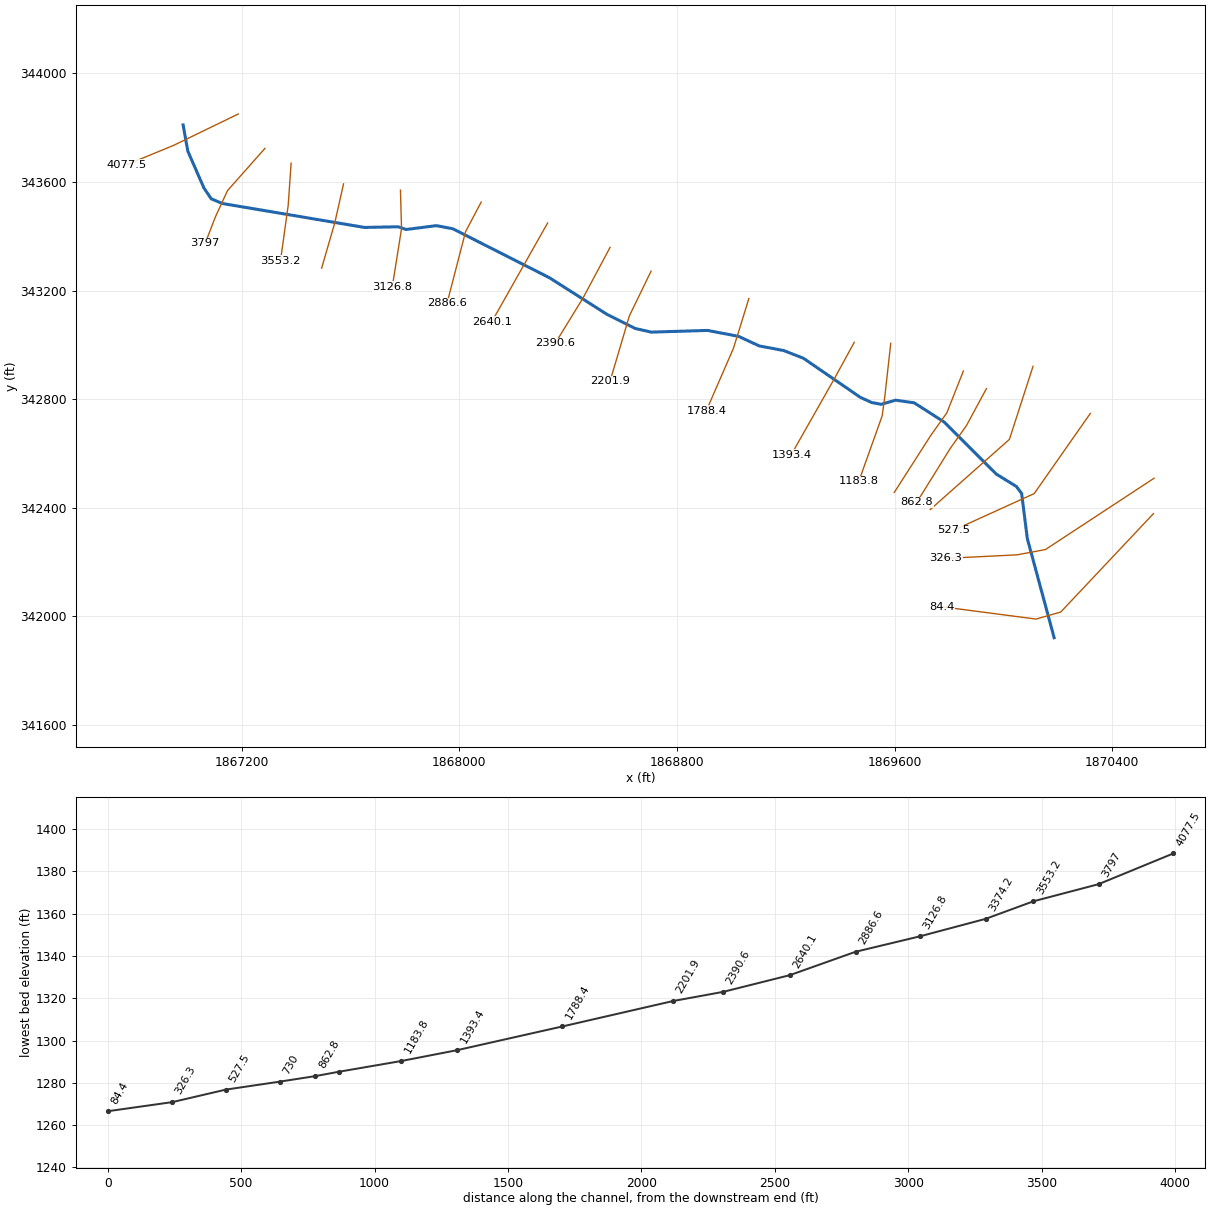
--- MARTINSRN.prj (project) ---

Proj Title=MARTINSRN
Current Plan=p01
Default Exp/Contr=0,0
English Units
Geom File=g01
Flow File=f01
Plan File=p01
BEGIN DESCRIPTION:
END DESCRIPTION:
DSS Export Rating Curves= 0
DSS Export Rating Curve Sorted= 0
DSS Export Volume Flow Curves= 0
DXF OffsetX= 0
DXF OffsetY= 0
DXF ScaleX= 0
DXF ScaleY= 0

--- MARTINSRN.p01 (plan) ---

Plan Title=Floodplain
Program Version=4.00
Geom File=g01
Flow File=f01
K Sum by GR=0
Std Step Tol=0.01
Critical Tol=0.01
Num of Std Step Trials=20
Max Error Tol=0.3
Flow Tol Ratio=0.001
Split Flow NTrial=30
Split Flow Tol=0.02
Split Flow Ratio=0.02
Log Output Level=0
Friction Slope Method=1
Unsteady Friction Slope Method=2
Unsteady Bridges Friction Slope Method=1
Global Log Level=0
CheckData=False
Run HTab=0
Run UNet=0
Run PostProcess=0
UNET Theta=0
UNET Theta Warmup=0
UNET ZTol=0
UNET ZSATol=0
UNET MxIter=0
UNET MaxInSteps=0
UNET DtIC=0
UNET DtMin=0
UNET MaxCRTS=0
UNET WFStab=0
UNET SFStab=0
UNET WFX=0
UNET SFX=0
UNET DSS MLevel=0
UNET DZMax Abort=0
UNET Convert EG Bridges=0
UNET Use Existing IB Tables=0
UNET Froude Limit=0
UNET Froude Power=0
Write IC File=0
Echo Input=False
Echo Output=False
Write Detailed=0

--- MARTINSRN.f01 (steady flow) ---

Flow Title=NFF Regression Equation
Program Version=4.00
Number of Profiles=1
Profile Names=P100yr
River Rch & RM=MARTINSRN,Main      ,4077.5
625.9637
River Rch & RM=MARTINSRN,Main      ,3797
661.1430
River Rch & RM=MARTINSRN,Main      ,84.4
726.9092
Boundary for River Rch & Prof#=MARTINSRN,Main      ,1
Up Type=0
Dn Type=3
Dn Slope=0.021993

--- MARTINSRN.g01 (geometry) ---

Geom Title=USGS 10m DEM
Program Version=4.10

River Reach=MARTINSRN       ,Main
Reach XY= 30
     1866984.914      343810.367      1867002.24      343713.627
     1867061.439      343577.903     1867088.151      343538.196
     1867129.301      343520.869     1867651.483      343432.712
     1867776.014      343435.103     1867804.478      343425.117
     1867915.859       343439.24     1867976.136      343427.938
     1868331.822      343247.165     1868543.143      343112.391
     1868646.814      343060.555     1868705.438      343047.133
      1868912.71       343053.36     1869026.917      343031.453
     1869102.438      342996.297     1869192.282       342979.37
     1869265.198      342950.724     1869473.758      342807.126
     1869516.066      342787.747     1869550.789      342781.236
     1869603.957      342796.427     1869672.316      342786.662
     1869781.994      342716.196     1869974.029       342524.16
     1870047.667      342478.679      1870067.16      342452.688
     1870087.898      342286.987     1870186.571      341921.586

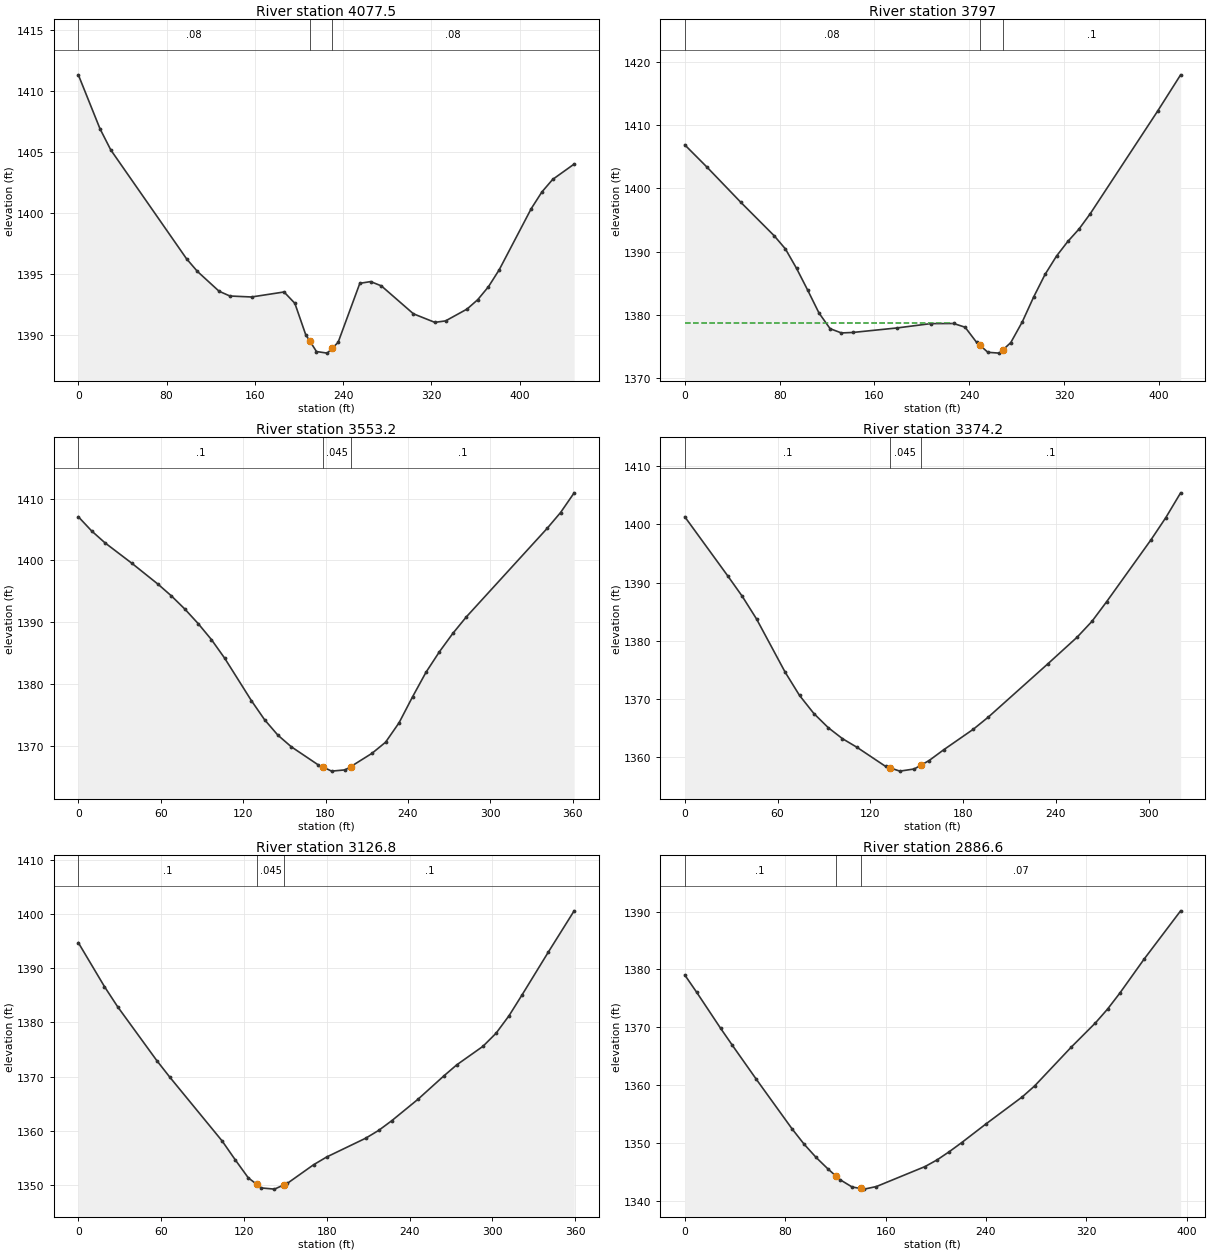
Type RM Length L Ch R = 1 ,4077.5  ,262.8,280.5,298
XS GIS Cut Line= 3
     1867187.623        343850.5     1866949.342      343734.615
     1866778.769      343664.302
#Sta/Elev= 30
       0 1411.34    19.6 1406.93    29.4 1405.19    98.1 1396.27     108 1395.23
   127.6 1393.61   137.4 1393.22     157 1393.14   186.5 1393.55   196.3 1392.62
   206.1 1390.06   209.9 1389.52   215.9 1388.67   225.7 1388.54   229.9 1388.92
   235.5 1389.42   255.2 1394.26     265  1394.4   274.7 1394.05   303.8 1391.76
   323.2 1391.06   332.9 1391.18   352.4 1392.15   362.1 1392.92   371.8 1393.98
   381.5 1395.36   410.6 1400.38   420.3 1401.75     430 1402.77   449.5 1404.03
#Mann= 3 , 0 , 0
       0     .08       0   209.9    .045       0   229.9     .08       0
#XS Ineff= 2 , 0
                          257.42         1394.18
Permanent Ineff=
       F       F
Bank Sta=209.9,229.9
XS Rating Curve= 0 ,0
Exp/Cntr=0.3,0.1

Type RM Length L Ch R = 1 ,3797    ,236.5,243.8,251.2
XS GIS Cut Line= 4
     1867285.713      343723.764     1867148.127      343568.382
     1867103.856      343472.028     1867066.095      343374.372
#Sta/Elev= 30
       0 1406.87    18.9 1403.32    47.2 1397.81    75.5  1392.5    84.9 1390.43
    94.3 1387.36   103.8 1383.88   113.2 1380.32   122.6 1377.84   132.1 1377.17
   141.5 1377.24   179.2 1377.96   207.5 1378.64   226.8 1378.66   236.5 1378.07
   246.1  1375.7   248.7 1375.27   255.7 1374.11   265.4 1373.98   268.7 1374.55
     275 1375.64   284.7 1378.91   294.3 1382.84   303.9  1386.4   313.6 1389.31
   323.1 1391.61   332.6 1393.58   342.1 1396.01   399.2 1412.29   418.3 1417.93
#Mann= 3 , 0 , 0
       0     .08       0   248.7    .045       0   268.7      .1       0
#XS Ineff= 2 , 0
          225.13 1378.74
Permanent Ineff=
       F       F
Bank Sta=248.7,268.7
XS Rating Curve= 0 ,0
Exp/Cntr=0.3,0.1

Type RM Length L Ch R = 1 ,3553.2  ,181.1,179.1,175.8
XS GIS Cut Line= 3
     1867381.957      343669.311     1867371.217      343514.671
     1867343.005      343310.678
#Sta/Elev= 30
       0 1407.06     9.7 1404.76    19.4 1402.84    38.8 1399.56    58.1 1396.13
    67.8 1394.24    77.5 1392.13    87.2 1389.78    96.9 1387.18   106.6 1384.15
     126  1377.3   135.6 1374.21   145.3 1371.71     155 1369.84   174.6 1366.91
   178.2 1366.54   184.4 1365.89   194.2 1366.09   198.2  1366.6   213.8 1368.77
   223.7 1370.57   233.5 1373.71   243.3  1377.9   253.1 1381.88   262.9 1385.21
   272.7 1388.19   282.5 1390.85   341.3 1405.17   351.1 1407.74     361 1410.93
#Mann= 3 , 0 , 0
       0      .1       0   178.2    .045       0   198.2      .1       0
Bank Sta=178.2,198.2
XS Rating Curve= 0 ,0
Exp/Cntr=0.3,0.1

Type RM Length L Ch R = 1 ,3374.2  ,240.6,247.3,250.4
XS GIS Cut Line= 3
     1867574.649      343593.165     1867542.136      343448.359
     1867494.138      343282.901
#Sta/Elev= 26
       0 1401.32    27.8 1391.15    37.1 1387.67    46.4 1383.75    64.9  1374.6
    74.2  1370.6    83.5 1367.48    92.8 1365.05     102 1363.16   111.3 1361.69
   129.9 1358.39   132.6 1358.15   139.1 1357.58   148.4 1357.95   152.6 1358.58
     158  1359.4   167.6 1361.28   186.7  1364.8   196.3 1366.87   234.6 1375.98
   253.7  1380.6   263.3 1383.32   272.8  1386.7   301.6 1397.39   311.1 1401.17
   320.7 1405.44
#Mann= 3 , 0 , 0
       0      .1       0   132.6    .045       0   152.6      .1       0
Bank Sta=132.6,152.6
XS Rating Curve= 0 ,0
Exp/Cntr=0.3,0.1

Type RM Length L Ch R = 1 ,3126.8  ,251.6,240.3,237.5
XS GIS Cut Line= 3
     1867783.835      343570.261     1867787.761      343428.251
     1867753.792      343213.789
#Sta/Elev= 27
       0  1394.7    18.9 1386.62    28.4 1382.92    56.8 1372.98    66.3  1369.9
   104.2 1358.14   113.6  1354.7   123.1 1351.36   129.3 1350.14   132.6 1349.49
   142.1 1349.27   149.3  1350.1   151.5 1350.35   170.4 1353.76   179.8 1355.18
   208.2 1358.66   217.6  1360.1     227 1361.87   245.9  1365.8   264.8 1370.14
   274.2 1372.19   293.1 1375.59   302.6    1378     312 1381.23   321.4 1385.05
   340.3 1392.89   359.2 1400.57
#Mann= 3 , 0 , 0
       0      .1       0   129.3    .045       0   149.3      .1       0
Bank Sta=129.3,149.3
XS Rating Curve= 0 ,0
Exp/Cntr=0.3,0.1

Type RM Length L Ch R = 1 ,2886.6  ,248.3,246.4,239.2
XS GIS Cut Line= 3
       1868080.7      343526.301     1868023.087      343416.961
     1867955.196      343154.055
#Sta/Elev= 28
       0 1379.03     9.5 1376.03    28.5 1369.82      38 1366.84      57 1360.99
    85.6 1352.38    95.1 1349.76   104.6 1347.48   114.1 1345.48   120.1 1344.32
   123.6 1343.64   133.3 1342.36   140.1  1342.1     143 1341.99   152.7 1342.44
   191.5  1345.9   201.2 1347.07   210.9 1348.49   220.6 1350.03     240 1353.27
     269 1357.96   278.8 1359.85   307.8 1366.52   327.2 1370.74   336.9 1373.14
   346.6 1375.88     366 1381.78   395.1 1390.13
#Mann= 3 , 0 , 0
       0      .1       0   120.1    .045       0   140.1     .07       0
Bank Sta=120.1,140.1
XS Rating Curve= 0 ,0
Exp/Cntr=0.3,0.1

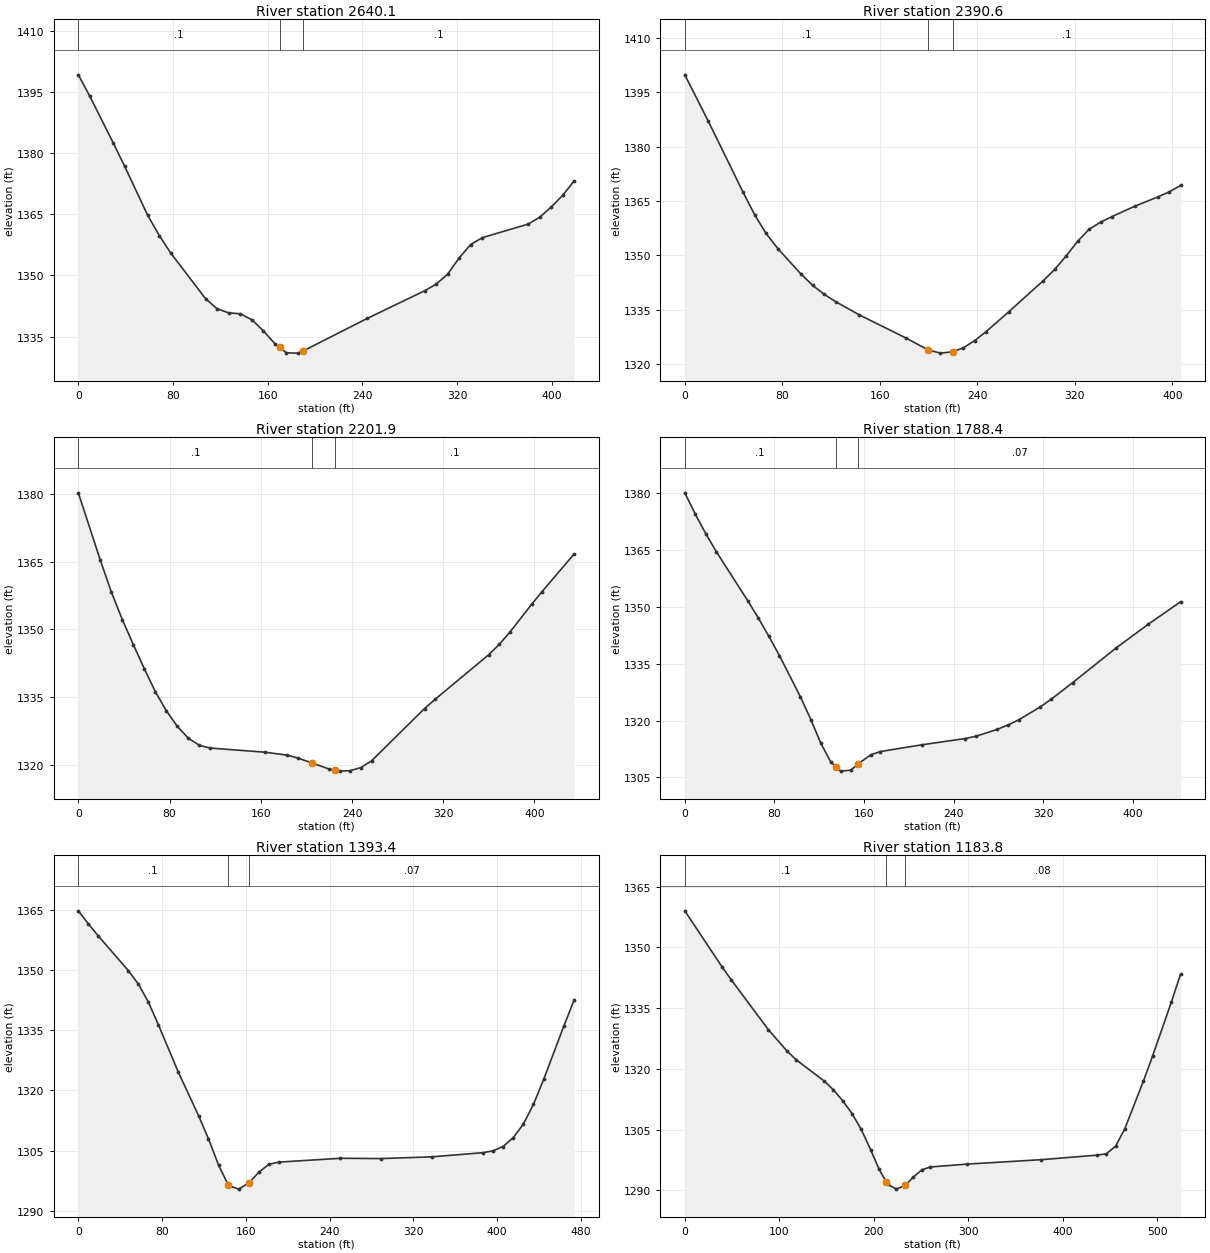
Type RM Length L Ch R = 1 ,2640.1  ,248.9,249.5,248.6
XS GIS Cut Line= 3
      1868324.74      343449.062     1868243.127      343304.391
     1868118.954      343084.279
#Sta/Elev= 30
       0 1399.22     9.8 1393.91    29.3 1382.61    39.1  1376.8    58.6 1364.74
    68.4 1359.76    78.2 1355.42   107.5 1344.27   117.2 1341.82     127 1340.81
   136.8 1340.57   146.6 1339.11   156.3 1336.38   166.1 1333.22     170 1332.32
   175.8 1330.99   185.5 1330.92     190 1331.47   243.9 1339.42   292.5 1346.22
   302.2 1347.84   311.9 1350.29   321.6 1354.25   331.3 1357.56   341.1 1359.24
     380  1362.6   389.7 1364.27   399.4 1366.76   409.1 1369.65   418.8  1373.2
#Mann= 3 , 0 , 0
       0      .1       0     170    .045       0     190      .1       0
Bank Sta=170,190
XS Rating Curve= 0 ,0
Exp/Cntr=0.3,0.1

Type RM Length L Ch R = 1 ,2390.6  ,183.6,188.7,195.4
XS GIS Cut Line= 3
     1868554.242      343359.259     1868455.646       343174.14
     1868352.754      343006.105
#Sta/Elev= 30
       0 1399.78    19.1 1387.11    47.7 1367.48    57.2 1361.25    66.7 1356.03
    76.3 1351.87    95.3 1344.84   104.9 1341.72   114.4 1339.24   123.9 1337.19
     143  1333.6   181.1 1327.25   199.7  1323.9   209.7 1323.02   219.7 1323.39
   228.5 1324.47   237.9 1326.49   247.3 1328.97     266 1334.48   294.2 1343.03
   303.6 1346.14     313 1349.87   322.3 1353.87   331.7 1357.17   341.1 1359.13
   350.5 1360.69   369.2 1363.55     388 1366.08   397.4 1367.49   406.8 1369.26
#Mann= 3 , 0 , 0
       0      .1       0   199.7    .045       0   219.7      .1       0
Bank Sta=199.7,219.7
XS Rating Curve= 0 ,0
Exp/Cntr=0.3,0.1

Type RM Length L Ch R = 1 ,2201.9  ,413.8,413.4,412.9
XS GIS Cut Line= 4
     1868704.984      343271.615     1868625.123      343106.685
     1868599.081      343018.143     1868553.943      342865.365
#Sta/Elev= 30
       0  1380.2    19.3 1365.29    28.9 1358.29    38.6 1352.16    48.2 1346.65
    57.9 1341.28    67.5 1336.25    77.2    1332    86.8 1328.57    96.4 1325.94
   106.1 1324.38   115.7 1323.76     164 1322.84   183.2 1322.19   192.5 1321.55
   205.3 1320.43   220.2  1319.1   225.3 1318.86   229.4 1318.66   238.6 1318.78
   247.8 1319.45   257.1 1320.93   303.6  1332.5     313 1334.57   359.9 1344.41
   369.2 1346.71   378.6 1349.45   397.4 1355.51   406.7 1358.37   434.8 1366.69
#Mann= 3 , 0 , 0
       0      .1       0   205.3    .045       0   225.3      .1       0
Bank Sta=205.3,225.3
XS Rating Curve= 0 ,0
Exp/Cntr=0.3,0.1

Type RM Length L Ch R = 1 ,1788.4  ,399.7,395,389.5
XS GIS Cut Line= 4
     1869064.359      343170.921     1869031.373      343063.282
     1869007.617      342987.264     1868908.109      342757.727
#Sta/Elev= 30
       0 1380.14     9.4 1374.51    18.8 1369.32    28.1 1364.61    56.3  1351.6
    65.7 1347.05      75 1342.26    84.4 1337.18   103.2 1326.27   112.6 1320.19
   121.4 1314.01   130.3 1309.04   134.6 1307.88   139.1 1306.66     148  1306.9
   154.6 1308.54   165.7 1310.94   174.5 1311.83   211.5 1313.61     250 1315.26
   259.6 1315.86   278.8 1317.68   288.4 1318.84   298.1 1320.23   317.3 1323.64
   326.9 1325.64   346.2 1330.05   384.7 1339.15   413.5 1345.44   442.4 1351.38
#Mann= 3 , 0 , 0
       0      .1       0   134.6    .045       0   154.6     .07       0
Bank Sta=134.6,154.6
XS Rating Curve= 0 ,0
Exp/Cntr=0.3,0.1

Type RM Length L Ch R = 1 ,1393.4  ,200.6,209.6,218.4
XS GIS Cut Line= 3
      1869451.79      343009.482     1869378.463      342875.198
     1869220.609      342596.268
#Sta/Elev= 30
       0 1364.72     9.6 1361.47    19.1 1358.46    47.8 1349.82    57.4 1346.47
    66.9    1342    76.5 1336.32    95.6 1324.49   114.8 1313.73   124.3 1307.95
   133.9 1301.41     143 1296.57   143.4 1296.36     153 1295.42     163 1296.98
   172.4 1299.64   182.1 1301.63   191.8 1302.15   250.1  1303.1     289 1303.03
   337.5 1303.46   386.1 1304.49   395.8 1304.94   405.5 1306.02   415.2  1308.2
   424.9 1311.58   434.6  1316.5   444.4 1322.76   463.8 1336.14   473.5 1342.53
#Mann= 3 , 0 , 0
       0      .1       0     143    .045       0     163     .07       0
Bank Sta=143,163
XS Rating Curve= 0 ,0
Exp/Cntr=0.3,0.1

Type RM Length L Ch R = 1 ,1183.8  ,245.1,233.7,221.9
XS GIS Cut Line= 4
     1869585.945      343005.846     1869564.244      342810.533
     1869554.513      342738.767     1869468.757      342498.033
#Sta/Elev= 30
       0 1359.06    39.3 1345.24    49.1 1342.03    88.4 1329.69   108.1 1324.42
   117.9 1322.24   147.4 1317.01   157.2 1314.82     167 1312.14   176.9 1308.96
   186.7 1305.02   196.5 1300.07   205.6 1295.16   213.1 1292.09   214.6 1291.48
   223.7 1290.28   233.1  1291.2   241.8 1293.27   250.8 1295.07   259.9 1295.76
   298.4 1296.46   377.1 1297.56     436 1298.68   445.9 1299.01   455.7 1300.89
   465.5 1305.23   485.2 1317.01     495 1323.29   514.7  1336.5   524.5 1343.47
#Mann= 3 , 0 , 0
       0      .1       0   213.1    .045       0   233.1     .08       0
Bank Sta=213.1,233.1
XS Rating Curve= 0 ,0
Exp/Cntr=0.3,0.1

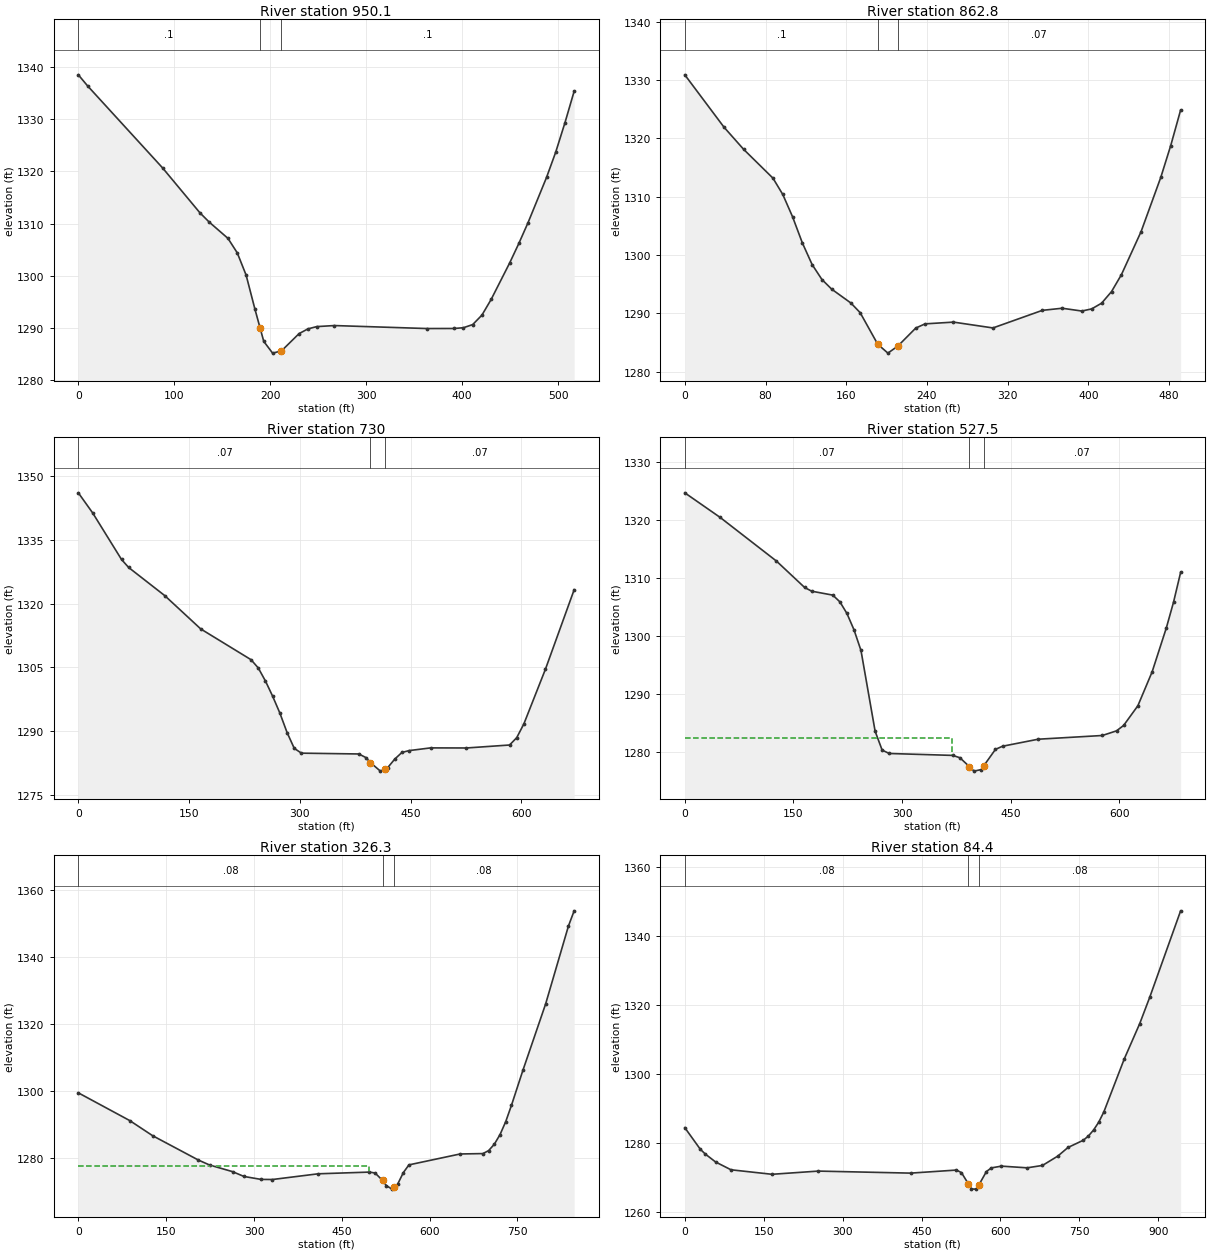
Type RM Length L Ch R = 1 ,950.1   ,87.1,87.3,87.5
XS GIS Cut Line= 4
     1869852.872      342903.849     1869792.108      342749.769
     1869733.514      342667.304     1869598.966      342456.801
#Sta/Elev= 30
       0  1338.5     9.7 1336.37    87.7 1320.69   126.7 1312.07   136.4 1310.29
   155.9 1307.18   165.6  1304.4   174.8 1300.15     184 1293.62   189.4    1290
   193.2 1287.45   202.4  1285.2   211.6 1285.62     230 1288.94   239.2 1289.84
   248.4 1290.28   266.8 1290.48   362.9 1289.91   391.7 1289.92   401.3 1290.07
   410.9 1290.67   420.5 1292.48   430.1 1295.48   449.4 1302.47     459 1306.22
   468.6 1310.21   487.8 1318.84   497.4  1323.7     507 1329.32   516.6 1335.36
#Mann= 3 , 0 , 0
       0      .1       0   189.4    .045       0   211.6      .1       0
Bank Sta=189.4,211.6
XS Rating Curve= 0 ,0
Exp/Cntr=0.3,0.1

Type RM Length L Ch R = 1 ,862.8   ,138.5,132.7,126.7
XS GIS Cut Line= 4
     1869937.507      342838.745     1869863.723      342702.026
     1869805.129      342619.561     1869681.431      342419.908
#Sta/Elev= 30
       0  1330.9    38.8 1321.93    58.3 1318.12    87.4 1313.17    97.1 1310.38
   106.8 1306.55   116.5 1302.07   126.2 1298.35   135.9 1295.79   145.6 1294.13
   164.6 1291.76   173.8  1290.1   191.2 1284.69   201.3 1283.16   211.2 1284.38
   228.9 1287.46   238.1 1288.18   266.3 1288.48   305.4 1287.48   354.4  1290.5
     374 1290.86   393.5 1290.38   403.3 1290.75   413.1 1291.73   422.9 1293.71
   432.7 1296.61   452.2    1304   471.8 1313.34   481.6 1318.77   491.4 1324.86
#Mann= 3 , 0 , 0
       0      .1       0   191.2    .045       0   211.2     .07       0
Bank Sta=191.2,211.2
XS Rating Curve= 0 ,0
Exp/Cntr=0.3,0.1

Type RM Length L Ch R = 1 ,730     ,210.1,202.6,195
XS GIS Cut Line= 3
     1870108.948       342921.21     1870022.143      342652.113
     1869731.344      342393.867
#Sta/Elev= 30
       0 1346.07    19.5 1341.32    58.5 1330.38    68.2 1328.49     117 1321.88
   165.8 1314.03     234 1306.78   243.8 1304.83   253.5 1301.76   263.2  1298.2
     273 1294.23   282.8 1289.63   292.5 1285.92   302.2 1284.78     380 1284.59
   389.7 1283.73   395.6 1282.58   409.2 1280.55   415.6 1281.06   418.9 1281.33
   428.6 1283.37   438.3 1284.94     448 1285.38   477.2 1286.02   525.8    1286
   584.2  1286.7   593.9 1288.43   603.6 1291.68   632.8 1304.55   671.7 1323.26
#Mann= 3 , 0 , 0
       0     .07       0   395.6    .045       0   415.6     .07       0
Bank Sta=395.6,415.6
XS Rating Curve= 0 ,0
Exp/Cntr=0.3,0.1

Type RM Length L Ch R = 1 ,527.5   ,206.8,201.2,194.1
XS GIS Cut Line= 3
     1870319.452      342747.599     1870113.289       342452.46
      1869818.15      342317.912
#Sta/Elev= 30
       0 1324.73    48.6 1320.51   126.5 1312.97   165.4 1308.42   175.1 1307.78
   204.3  1307.1   214.1 1305.94   223.8 1303.94   233.5 1301.14   243.2 1297.56
   262.7 1283.65   272.4 1280.39   282.2 1279.81   369.8 1279.48   379.7 1279.08
   392.9 1277.54   399.3 1276.77   409.2 1277.04   412.9 1277.73   428.8 1280.52
   438.6 1281.06   487.8 1282.27   576.3 1282.91   595.9 1283.71   605.7 1284.64
   625.4 1288.04   645.1 1293.89   664.7 1301.46   674.6 1305.88   684.4 1311.02
#Mann= 3 , 0 , 0
       0     .07       0   392.9    .045       0   412.9     .07       0
#XS Ineff= 2 , 0
          368.94 1282.46
Permanent Ineff=
       F       F
Bank Sta=392.9,412.9
XS Rating Curve= 0 ,0
Exp/Cntr=0.3,0.1

Type RM Length L Ch R = 1 ,326.3   ,239.6,241.9,244.3
XS GIS Cut Line= 4
     1870553.827      342508.884     1870154.521      342246.297
     1870050.355      342226.766     1869787.768      342213.745
#Sta/Elev= 30
       0 1299.55    87.8 1291.28   126.8 1286.78   204.8 1279.53   224.3 1278.02
   263.3 1276.06   282.8 1274.62   312.1 1273.74   331.6 1273.71   409.6 1275.41
   497.2 1275.92   506.8 1275.65   519.5 1273.45   526.1 1271.89   535.7 1270.84
   539.5 1271.42   545.4 1272.33     555 1275.75   564.6 1278.07     652 1281.32
     691 1281.44   700.7 1282.32   710.5 1284.24   720.2  1287.1     730    1291
   739.7 1295.82   759.2 1306.23   798.1 1326.07   837.1 1349.32   846.8 1353.82
#Mann= 3 , 0 , 0
       0     .08       0   519.5    .045       0   539.5     .08       0
#XS Ineff= 2 , 0
          495.64 1277.76
Permanent Ineff=
       F       F
Bank Sta=519.5,539.5
XS Rating Curve= 0 ,0
Exp/Cntr=0.3,0.1

Type RM Length L Ch R = 1 ,84.4    ,83.3,84.4,85.5
XS GIS Cut Line= 4
     1870551.657      342378.676     1870210.945      342016.262
     1870119.799      341990.221     1869772.577      342035.794
#Sta/Elev= 30
       0 1284.39    29.3 1278.15      39 1276.72    58.5 1274.42    87.8 1272.15
   165.8 1270.84   253.6 1271.77   429.2 1271.18   516.4 1272.07   525.9 1271.31
     539 1268.05   544.8 1266.56   554.3 1266.53     559 1267.77   573.3 1271.64
   582.7  1272.7   601.9 1273.21   650.6 1272.72   679.8 1273.41     709 1276.13
   728.4 1278.64   757.6 1280.74   767.3 1281.99     777 1283.71   786.8 1285.99
   796.5 1288.97   835.4  1304.4   864.6 1314.59     884  1322.4   942.4 1347.38
#Mann= 3 , 0 , 0
       0     .08       0     539    .045       0     559     .08       0
Bank Sta=539,559
XS Rating Curve= 0 ,0
Exp/Cntr=0.3,0.1

Chan Stop Cuts=-1
Use User Specified Reach Order=0
Composite Channel Slope=5